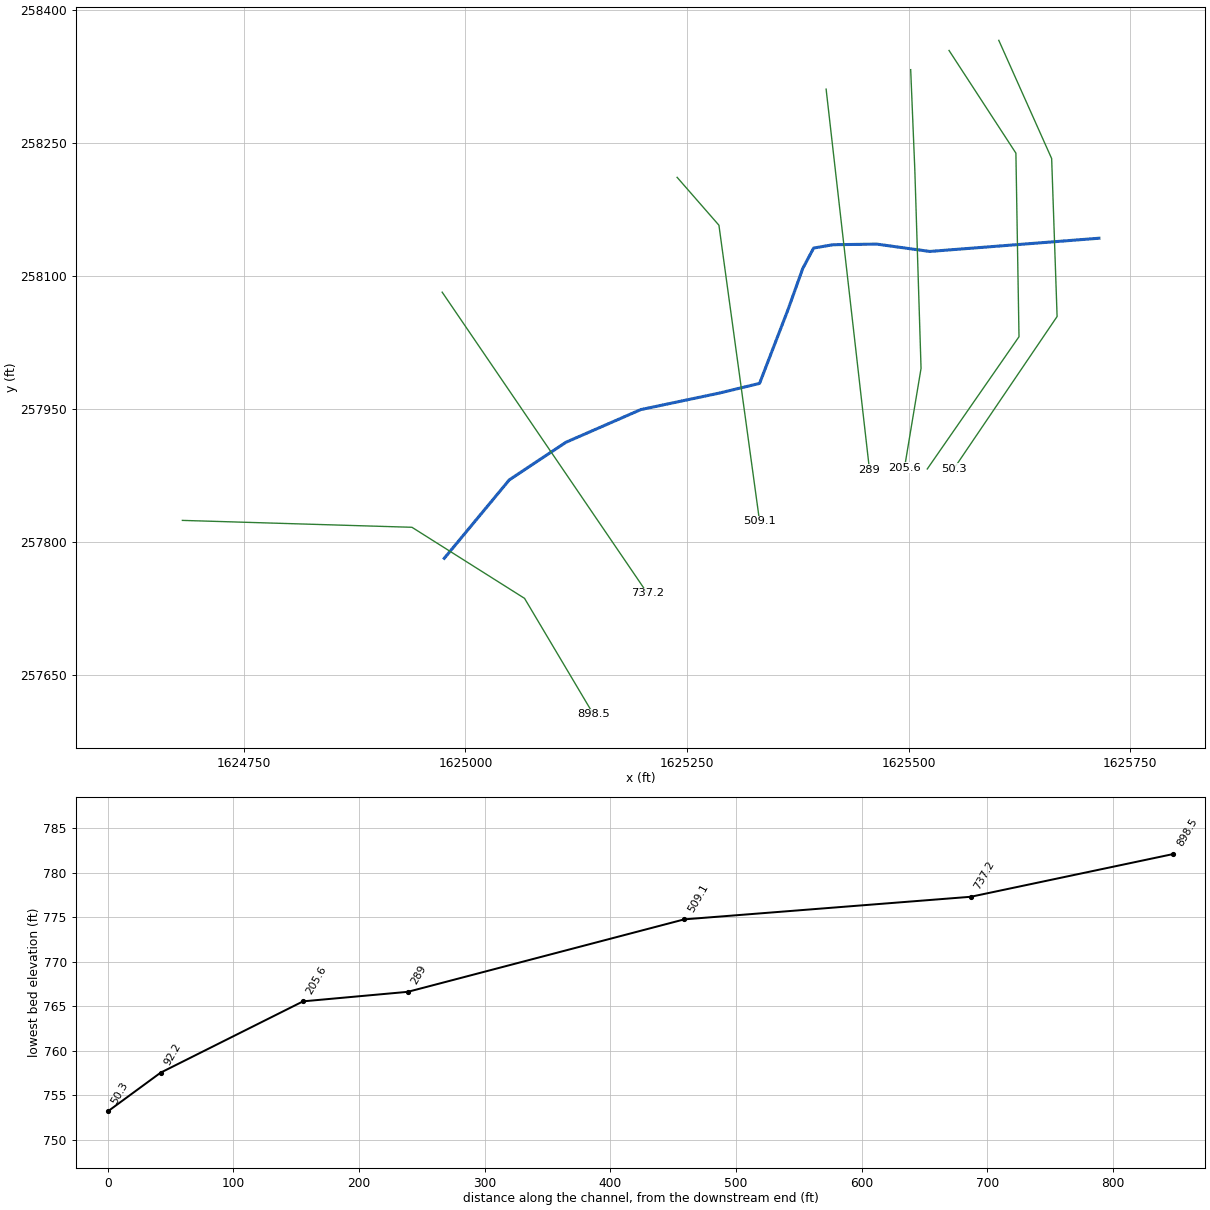
--- stnclbrnch.prj (project) ---

Proj Title=stnclbrnch
Current Plan=p01
Default Exp/Contr=0,0
English Units
Geom File=g01
Flow File=f01
Plan File=p01
BEGIN DESCRIPTION:
END DESCRIPTION:
DSS Export Rating Curves= 0
DSS Export Rating Curve Sorted= 0
DSS Export Volume Flow Curves= 0
DXF OffsetX= 0
DXF OffsetY= 0
DXF ScaleX= 0
DXF ScaleY= 0

--- stnclbrnch.p01 (plan) ---

Plan Title=Approximate Study  - 100yr
Program Version=4.00
Geom File=g01
Flow File=f01
Subcritical Flow
K Sum by GR= 0
Std Step Tol= 0.01
Critical Tol= 0.01
Num of Std Step Trials= 20
Max Error Tol= 0.3
Flow Tol Ratio= 0.001
Split Flow NTrial= 30
Split Flow Tol= 0.02
Split Flow Ratio= 0.02
Log Output Level= 0
Friction Slope Method= 1
Unsteady Friction Slope Method= 2
Unsteady Bridges Friction Slope Method= 1
Parabolic Critical Depth
Global Vel Dist= 0 , 0 , 0
Global Log Level= 0
CheckData=True
Encroach Param=-1 ,0,0, 0
Run HTab= 0
Run UNet= 0
Run PostProcess= 0
Run WQNet= 0
UNET Theta= 0
UNET Theta Warmup= 0
UNET ZTol= 0
UNET ZSATol= 0
UNET MxIter= 0
UNET MaxInSteps= 0
UNET DtIC= 0
UNET DtMin= 0
UNET MaxCRTS= 0
UNET WFStab= 0
UNET SFStab= 0
UNET WFX= 1
UNET SFX= 1
UNET DSS MLevel= 1
UNET DZMax Abort= 0
UNET Convert EG Bridges= 0
UNET Use Existing IB Tables= 0
UNET Froude Reduction=False
UNET Froude Limit= 0
UNET Froude Power= 0
UNET Time Slicing=0,0, 5
Write IC File= 0
Echo Input=False
Echo Output=False
Write Detailed= 0
Detailed Automatic Start=False, 0
WQ ULTIMATE=-1
WQ Max Comp Step=1HOUR
WQ Output Interval=15MIN
WQ Output Selected Increments= 0
WQ Output face flow=0
WQ Output face velocity=0
WQ Output face area=0
WQ Output face dispersion=0
WQ Output cell volume=0
WQ Output cell surface area=0
WQ Output cell continuity=0
WQ Output face conc=0
WQ Output face dconc_dx=0
WQ Output face courant=0
WQ Output face peclet=0
WQ Output face adv mass=0
WQ Output face disp mass=0
WQ Output cell mass=0
WQ Output cell source sink temp=0
WQ Output cell source sink nsm=0
WQ Output MaxMinRange=-1
WQ Daily Max Min Mean=-1
WQ Daily Range=0
WQ Daily Time=0
WQ Create Restart=0
WQ Fixed Restart=0
WQ System Summary=False
Sorting and Armoring Iterations= 10
XS Update Threshold= 0.02
Hydraulics Update Threshold= 0.02
Energy Slope Method= 1
Volume Change Method= 0
XS Weighting Method= 0
Number of US Weighted Cross Sections= 1
Number of DS Weighted Cross Sections= 1
Upstream XS Weight=0.25
Main XS Weight=0.5
Downstream XS Weight=0.25
Number of DS XS's Weighted with US Boundary= 1
Upstream Boundary Weight= 1
Weight of XSs Associated with US Boundary= 0
Number of US XS's Weighted with DS Boundary= 1
Downstream Boundary Weight= 0.5
Weight of XSs Associated with DS Boundary= 0.5
Sediment Output Level= 4
Mass or Volume Output= 0
Output Increment Type= 1
Profile and TS Output Increment= 10
XS Output Flag= 0
XS Output Increment= 10
Disregard all LS=0
Disregard all Conn=0
Disregard all Breaches=0
Disregard all Pumps=0

--- stnclbrnch.f01 (steady flow) ---

Flow Title=USGS Regression Equation
Program Version=4.00
Number of Profiles= 1
Profile Names=P100yr
River Rch & RM=stnclbrnch,Main            ,898.5
     384
River Rch & RM=stnclbrnch,Main            ,289
     389
Boundary for River Rch & Prof#=stnclbrnch,Main            , 1
Up Type= 0
Dn Type= 3
Dn Slope=0.062471
DSS Import GetInterval= 0
DSS Import GetPeak= 0
DSS Import FillOption= 0

--- stnclbrnch.g01 (geometry) ---

Geom Title=USGS 3m DEM
Program Version=4.00

River Reach=stnclbrnch      ,Main
Reach XY= 14
     1624976.157      257781.441     1625010.692       257823.06
     1625049.513      257869.874     1625113.255      257912.157
     1625197.785      257949.045      1625285.96      257967.573
     1625331.791      257978.586     1625363.899      258061.809
     1625380.448      258107.992     1625392.773      258131.154
     1625414.551      258134.905     1625463.936      258135.616
     1625523.829      258127.341     1625714.639      258142.238

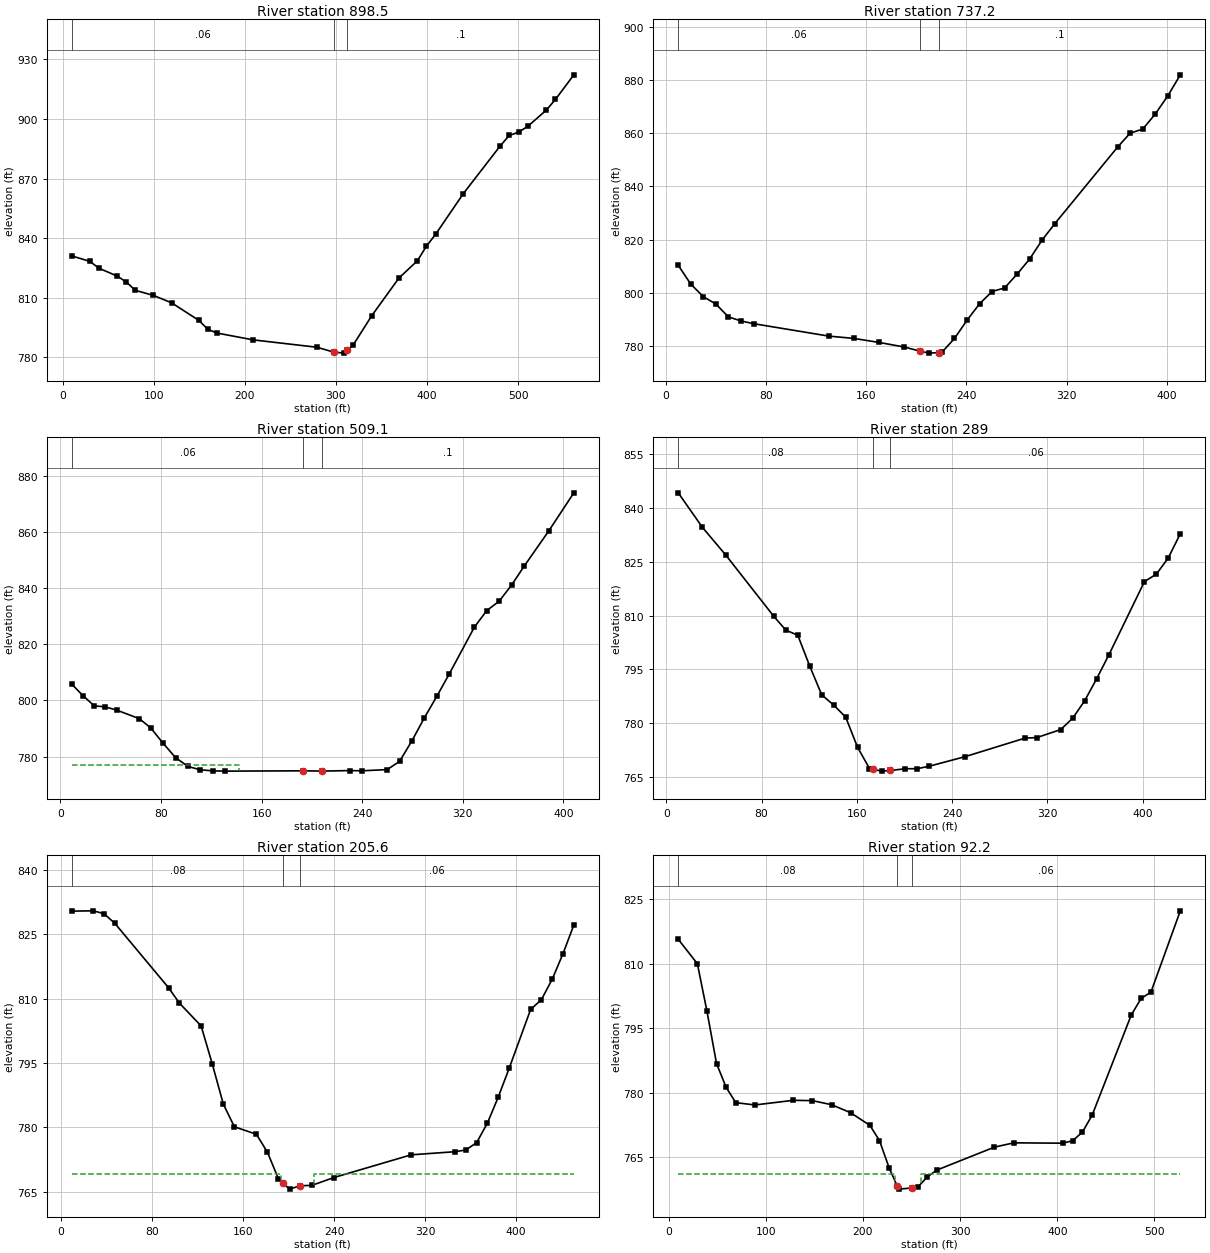
Type RM Length L Ch R = 1 ,898.5   ,170.6,161.3,152.1
XS GIS Cut Line= 4
     1624680.686      257824.149     1624939.665       257816.38
     1625066.668      257736.261     1625144.258      257605.744
#Sta/Elev= 30
      10  831.05    29.9  828.29    39.9  824.84    59.8  820.91    69.8  817.95
    79.7  813.73    99.7  811.16   119.6  807.44   149.5   798.6   159.4  794.11
   169.4  792.23   209.3  788.79   279.1  785.09   297.6 782.637   309.1  782.13
   312.6 783.614   319.2  786.42   339.2  800.92   369.2  819.96   389.2  828.51
   399.2  835.89   409.3  841.87   439.6  862.27   480.1   886.3   490.2  891.65
   500.4  893.31   510.5  896.23   530.7  904.34   540.9  909.78   561.1  922.17
#Mann= 3 , 0 , 0
      10     .06       0   297.6    .045       0   312.6      .1       0
Bank Sta=297.6,312.6
XS Rating Curve= 0 ,0
Exp/Cntr=0.3,0.1

Type RM Length L Ch R = 1 ,737.2   ,238.5,228.1,217.7
XS GIS Cut Line= 2
     1624973.764      258081.402     1625205.118       257742.14
#Sta/Elev= 30
      10  810.32      20  803.26      30  798.55    40.1  795.73    50.1  790.93
    60.1  789.41    70.1  788.39   130.2  783.71   150.2  782.85   170.3  781.33
   190.3  779.62   202.8  778.08   210.3  777.32   217.8  777.53   220.3   777.6
   230.4  782.82   240.4  789.67   250.4  795.85   260.4  800.47   270.4  801.82
   280.4  807.03   290.5  812.76   300.5  819.93   310.5  825.99   360.6  854.78
   370.6  860.01   380.6   861.5   390.6  867.16   400.6     874   410.6  881.91
#Mann= 3 , 0 , 0
      10     .06       0   202.8    .045       0   217.8      .1       0
Bank Sta=202.8,217.8
XS Rating Curve= 0 ,0
Exp/Cntr=0.3,0.1

Type RM Length L Ch R = 1 ,509.1   ,220.2,220.1,219.6
XS GIS Cut Line= 3
     1625238.785      258210.891     1625285.945      258156.903
     1625331.766      257823.371
#Sta/Elev= 30
       9  805.83    17.9  801.72    26.9  798.09    35.8   797.7    44.8  796.55
    62.7  793.51    71.7  790.25    81.6  784.75    91.5  779.62   101.4  776.44
   111.3  775.25   121.2  774.88   131.1  774.78   192.9  774.89   207.9   774.8
   230.1  774.97     240   774.9   259.8  775.32   269.7  778.25   279.6  785.67
   289.5  793.87   299.4  801.55   309.3  809.54   329.1  826.11     339  832.08
   348.9  835.43   358.8  841.21   368.7  847.89   388.5  860.63   408.3  874.13
#Mann= 3 , 0 , 0
       9     .06       0   192.9    .045       0   207.9      .1       0
#XS Ineff= 2 , 0
       0     142     777               0
Permanent Ineff=
       F       F
Bank Sta=192.9,207.9
XS Rating Curve= 0 ,0
Exp/Cntr=0.3,0.1

Type RM Length L Ch R = 1 ,289     ,85.2,83.4,81.5
XS GIS Cut Line= 2
     1625406.857      258310.319     1625455.746      257881.515
#Sta/Elev= 30
      10  844.26    30.1  834.72    50.2  826.78    90.3  809.79   100.4  805.95
   110.4  804.53   120.4  795.95   130.5   787.9   140.5  785.07   150.6   781.7
   160.6  773.27   170.6  767.36   173.2  767.18   180.7  766.63   188.2  766.81
   200.7  767.29   210.8  767.32   220.8     768   250.9  770.67   301.1  775.83
   311.1  775.99   331.2  778.23   341.3  781.42   351.3  786.27   361.3  792.36
   371.4  798.92   401.5  819.51   411.5  821.58   421.5   826.1   431.6  832.86
#Mann= 3 , 0 , 0
      10     .08       0   173.2    .045       0   188.2     .06       0
Bank Sta=173.2,188.2
XS Rating Curve= 0 ,0
Exp/Cntr=0.3,0.1

Type RM Length L Ch R = 1 ,205.6   ,113.7,113.4,113
XS GIS Cut Line= 4
     1625502.259      258332.293     1625506.936      258218.874
     1625513.951      257995.545     1625495.243      257883.296
#Sta/Elev= 30
     9.5   830.4    28.4  830.47    37.8  829.81    47.3  827.57    94.6  812.52
   104.1  808.95   123.2  803.62   132.9  794.84   142.7   785.4   152.4  780.11
   171.8  778.35   181.5  774.16   191.2  767.93   195.4 766.902   200.9  765.56
   210.4 766.355   220.4  766.43   239.8  768.25   307.8  773.56   346.4  774.29
   355.9  774.69   365.4  776.42   374.9     781   384.4  787.06   393.9  793.71
   412.8  807.46   422.3  809.76   431.8  814.52   441.3   820.5   450.8  827.17
#Mann= 3 , 0 , 0
     9.5     .08       0   195.4    .045       0   210.4     .06       0
#XS Ineff= 2 , 0
       0     193     769     222       0     769
Permanent Ineff=
       F       F
Bank Sta=195.4,210.4
XS Rating Curve= 0 ,0
Exp/Cntr=0.3,0.1

Type RM Length L Ch R = 1 ,92.2    ,41.6,42,42.3
XS GIS Cut Line= 4
     1625545.521      258353.924     1625620.939      258238.167
     1625624.447      258031.208     1625520.967      257882.127
#Sta/Elev= 30
     9.9  815.72    29.6  810.03    39.5  798.92    49.3  786.79    59.2  781.24
    69.1  777.68    88.8  777.14   128.3  778.22     148  778.15   167.7   777.2
   187.4  775.33   207.2  772.37     217  768.85   226.9  762.51   235.2   758.3
   236.7  757.54   250.2 757.804   256.4     758   266.3   760.4   276.2  761.99
   335.3  767.32   355.2  768.32   405.6  768.24   415.7   768.8   425.8  770.79
   435.9  774.78   476.2  798.13   486.3  801.95   496.4  803.44   526.6  822.35
#Mann= 3 , 0 , 0
     9.9     .08       0   235.2    .045       0   250.2     .06       0
#XS Ineff= 2 , 0
       0     233     761     260       0     761
Permanent Ineff=
       F       F
Bank Sta=235.2,250.2
XS Rating Curve= 0 ,0
Exp/Cntr=0.3,0.1

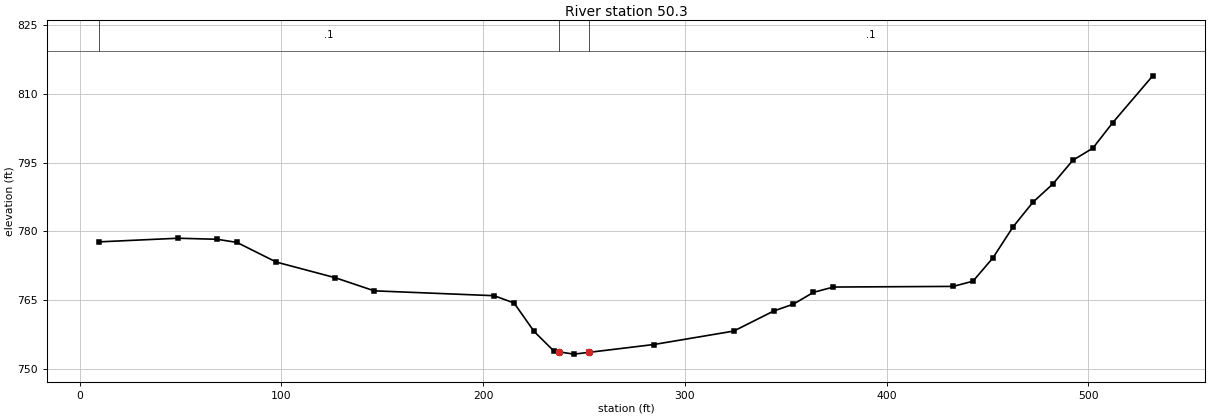
Type RM Length L Ch R = 1 ,50.3    ,49.3,50.3,51.3
XS GIS Cut Line= 4
     1625601.646      258365.325     1625661.278      258232.029
     1625667.417      258054.008     1625550.783      257882.127
#Sta/Elev= 30
     9.7  777.69    48.7  778.48    68.1  778.25    77.9  777.57    97.4  773.28
   126.6  769.87     146     767   205.4  765.94   215.3  764.34   225.2  758.15
   235.1  753.83   237.5  753.68     245  753.19   252.5  753.58   284.6  755.29
   324.2  758.22   343.9  762.58   353.8  764.11   363.7  766.67   373.6  767.83
     433  767.97   442.8  769.11   452.7  774.21   462.6  780.93   472.5  786.34
   482.4  790.33   492.3   795.5   502.2  798.13   512.1  803.72   531.9  813.92
#Mann= 3 , 0 , 0
     9.7      .1       0   237.5    .045       0   252.5      .1       0
Bank Sta=237.5,252.5
XS Rating Curve= 0 ,0
Exp/Cntr=0.3,0.1

Chan Stop Cuts=-1
Use User Specified Reach Order=0